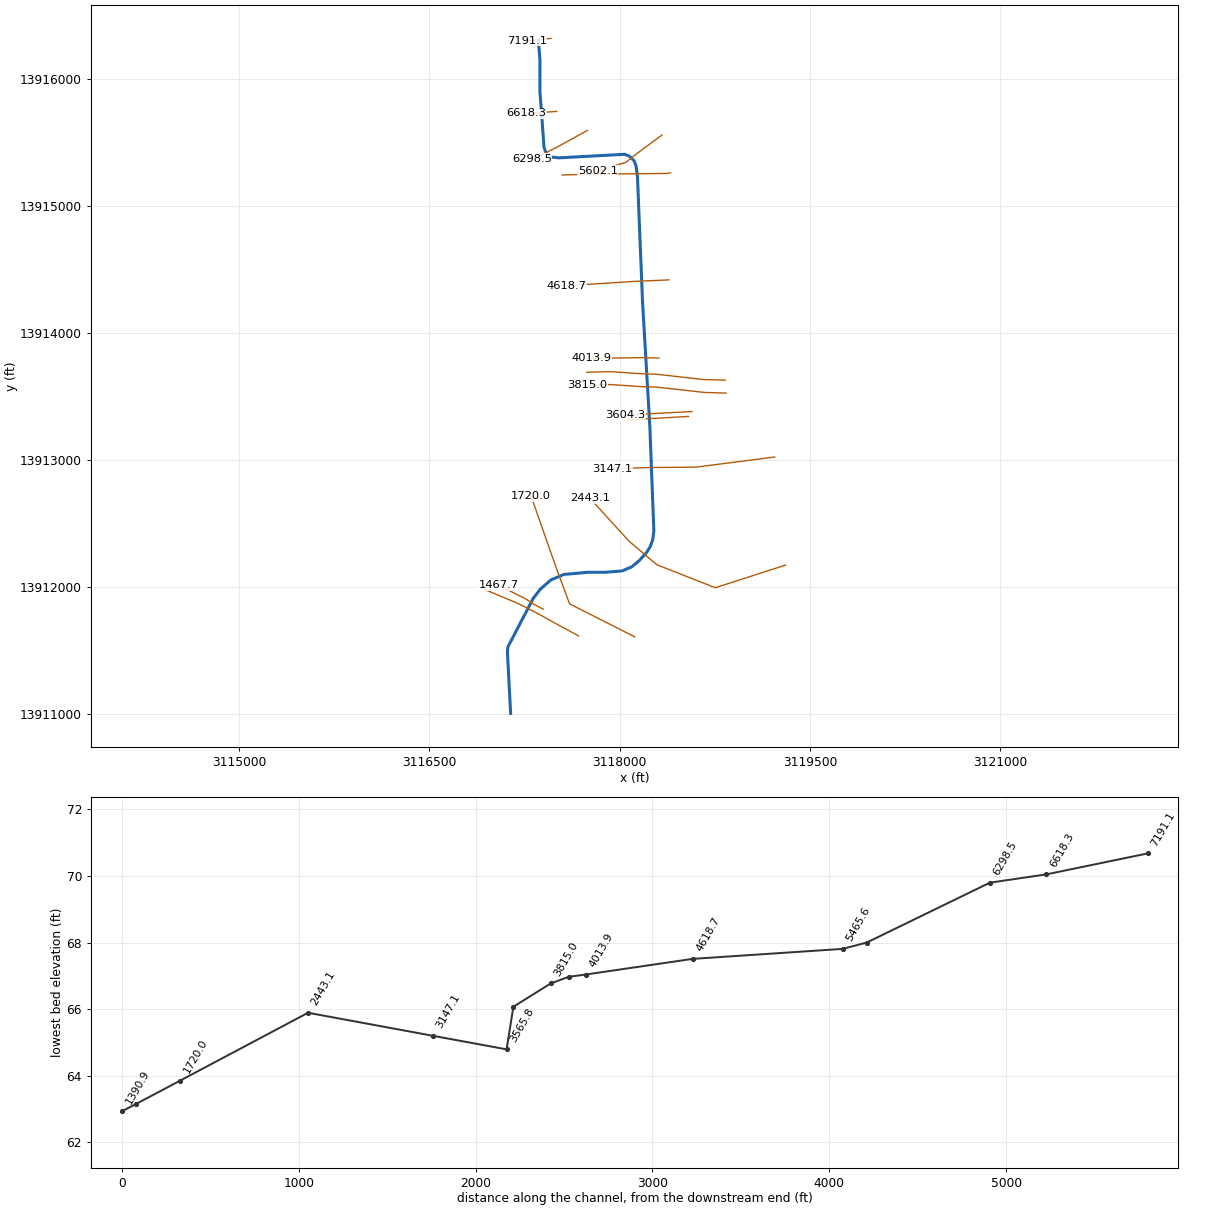
--- P155-00-00.PRJ (project) ---

Proj Title=P155-00-00
Current Plan=p02
Default Exp/Contr=.3,.1
English Units
Geom File=g01
Flow File=f02
Flow File=f01
Plan File=p04
Plan File=p03
Plan File=p02
Plan File=p01
Y Axis Title=Elevation
X Axis Title(PF)=Main Channel Distance
X Axis Title(XS)=Station
BEGIN DESCRIPTION:
Greens Bayou Watershed
P155-00-00
HCFCD Unit P155-00-00
Flood Hazard Model
10, 2, 1, 0.2% Event
Filename P155-00-00.prj
Prepared by:  Watershed Concepts  Date:
Reviewed by:                      Date:
STATUS FINAL
END DESCRIPTION:
DSS Export Rating Curves= 0
DSS Export Rating Curve Sorted= 0
DSS Export Volume Flow Curves= 0
DXF OffsetX= 0
DXF OffsetY= 0
DXF ScaleX= 1
DXF ScaleY= 10

--- P155-00-00.p02 (plan) ---

Plan Title=Floodway
Version=Version 3.0.1  Mar 2001
Short Identifier=Floodway060
Geom File=g01
Flow File=f02
Subcritical Flow
K Sum by GR= 0
Std Step Tol= 0.01
Critical Tol= 0.01
Num of Std Step Trials= 20
Max Error Tol= 0.3
Flow Tol Ratio= 0.001
Split Flow NTrial= 30
Split Flow Tol= 0.02
Split Flow Ratio= 0.02
Log Output Level= 0
Friction Slope Method= 1
Unsteady Friction Slope Method= 2
Parabolic Critical Depth
Global Vel Dist= 0 , 0 , 0
Global Log Level= 0
CheckData=True
Encroach Param=-1 ,0,0, 2
Encroach River=P155-00-00
Encroach Reach=Reach - 1
Encroach Node=7191.1
       1  4945.4  5049.9
Encroach Node=6618.3
       1  4947.3  5053.7
Encroach Node=6298.5
       1  4947.3  5053.7
Encroach Node=5602.1
       1  4945.7  5050.2
Encroach Node=5465.6
       1  4945.7  5050.2
Encroach Node=4618.7
       1  4941.6  5047.4
Encroach Node=4013.9
       1  4948.5  5049.5
Encroach Node=3917.0
       1  4948.5  5049.5
Encroach Node=3866.0
       1  4948.5  5049.5
Encroach Node=3815.0
       1  4948.5  5049.5
Encroach Node=3604.3
       1  4949.9  5049.4
Encroach Node=3583.9
       1  4949.9  5049.4
Encroach Node=3565.8
       1  4950.9  5050.3
Encroach Node=3147.1
       1 4948.35 5051.65
Encroach Node=2443.1
       1 4948.35 5051.65
Encroach Node=1720.0
       1    4963    5060
Encroach Node=1467.7
       1    4956    5049
Encroach Node=1390.9
       1    4970    5030
Encroach Node=1324.6
       1    4970    5030
Encroach Node=1258.3
       1    4970    5030
Encroach Node=1141.6
       1    4950    5050
Encroach Node=1124.5
       1    4950    5050
Encroach Node=1107.4
       1    4950    5050
Encroach Node=898.1
       1    4925    5050
Encroach Node=840.2
       1    4966    5028
Encroach Node=812.0
       1    4966    5028
Encroach Node=783.8
       1    4966    5028
Encroach Node=513.6
       1  4975.1    5025
Encroach Reach=P155-00-00_0005
Encroach Node=7191.1
       1  4945.4  5049.9
Encroach Node=6618.3
       1  4947.3  5053.7
Encroach Node=6298.5
       1  4947.3  5053.7
Encroach Node=5602.1
       1  4945.7  5050.2
Encroach Node=5465.6
       1  4945.7  5050.2
Encroach Node=4618.7
       1  4941.6  5047.4
Encroach Node=4013.9
       1  4948.5  5049.5
Encroach Node=3917.0
       1  4948.5  5049.5
Encroach Node=3866.0
       1  4948.5  5049.5
Encroach Node=3815.0
       1  4948.5  5049.5
Encroach Node=3604.3
       1  4949.9  5049.4
Encroach Node=3583.9
       1  4949.9  5049.4
Encroach Node=3565.8
       1  4950.9  5050.3
Encroach Node=3147.1
       1 4948.35 5051.65
Encroach Node=2443.1
       1 4948.35 5051.65
Encroach Node=1720.0
       1    4963    5060
Encroach Node=1467.7
       1    4956    5049
Encroach Node=1390.9
       1    4970    5030
Encroach Node=1324.6
       1    4970    5030
Encroach Node=1258.3
       1    4970    5030
Encroach Node=1141.6
       1    4950    5050
Encroach Node=1124.5
       1    4950    5050
Encroach Node=1107.4
       1    4950    5050
Encroach Node=898.1
       1    4925    5050
Encroach Node=840.2
       1    4966    5028
Encroach Node=812.0
       1    4966    5028
Encroach Node=783.8
       1    4966    5028
Encroach Node=513.6
       1  4975.1    5025
Computation Interval=1HOUR
Output Interval=1HOUR
Run HTab= 0
Run UNet= 0
Run PostProcess= 0
UNET Theta= 1
UNET ZTol= 0.02
UNET ZSATol= 0.1
UNET MxIter= 20
UNET MaxInSteps= 20
UNET DtIC= 0
UNET DtMin= 0
UNET MaxCRTS= 20
UNET WFStab= 2
UNET SFStab= 1
UNET WFX= 1
UNET SFX= 1
UNET Convert EG Bridges=-1
UNET Use Existing IB Tables=-1
Instantaneous Interval=1HOUR
Write IC File= 0
IC Time=0
Write Velocity= 0
Write Detailed= 0

--- P155-00-00.p01 (plan) ---

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Plan Title=FEMA Effective June 2007
Short Identifier=FEMAeff0607
Geom File= g01
Flow File= f01
Interactive Comp Mode
Encroach Param= -1, 0, 0, 0

--- P155-00-00.p03 (plan) ---

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Plan Title=Floodway-Revised 081709
Short Identifier=Fldway-K WS
Geom File=g01
Flow File=f03
BEGIN DESCRIPTION:
Revised BC to Known WS (PBS&J Aug 09)
END DESCRIPTION:

--- P155-00-00.p04 (plan) ---

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Plan Title=FEMA Effective - Revised 081709
Short Identifier=FEMAeffBCkWS
Geom File=g01
Flow File=f01
Encroach Param=-1 ,0,0, 0
BEGIN DESCRIPTION:
Revised BC to Known WS (PBS&J - Aug 09)
END DESCRIPTION:

--- P155-00-00.f02 (steady flow) ---

Flow Title= Floodway
Number of Profiles= 2
Profile Names=1PCT_100yr, 1PCTFloodway_100yrFW
River Rch & RM=P155-00-00,P155-00-00_0005,7191.1
    1213    1213
River Rch & RM=P155-00-00,P155-00-00_0005,6618.3
    1261    1261
River Rch & RM=P155-00-00,P155-00-00_0005,6298.5
    1370    1370
River Rch & RM=P155-00-00,P155-00-00_0005,5602.1
    1393    1393
River Rch & RM=P155-00-00,P155-00-00_0005,5465.6
    1542    1542
River Rch & RM=P155-00-00,P155-00-00_0005,4618.7
    1658    1658
River Rch & RM=P155-00-00,P155-00-00_0005,4013.9
    1677    1677
River Rch & RM=P155-00-00,P155-00-00_0005,3917
    2357    2357
River Rch & RM=P155-00-00,P155-00-00_0005,3147.1
    2503    2503
River Rch & RM=P155-00-00,P155-00-00_0005,2443.1
    2604    2604
River Rch & RM=P155-00-00,P155-00-00_0005,1720
    2651    2651
River Rch & RM=P155-00-00,P155-00-00_0005,1390.9
    2692    2692
River Rch & RM=P155-00-00,P155-00-00_0005,1141.6
    2740    2740
River Rch & RM=P155-00-00,P155-00-00_0005,840.2
    2781    2781
Boundary for River Rch & Prof#=P155-00-00,P155-00-00_0005, 1
Up Type= 0
Dn Type= 3
Dn Slope= 0.00130
Boundary for River Rch & Prof#=P155-00-00,P155-00-00_0005, 2
Up Type= 0
Dn Type= 1
Dn Known WS=73.39

--- P155-00-00.f01 (steady flow) ---

Flow Title= FEMA Effective June 2007
Number of Profiles= 4
Profile Names=10PCT_10yr, 2PCT_50yr, 1PCT_100yr, 0.2PCT_500yr
River Rch & RM=P155-00-00,P155-00-00_0005,7191.1
     744    1062    1213    1714
River Rch & RM=P155-00-00,P155-00-00_0005,6618.3
     773    1103    1261    1779
River Rch & RM=P155-00-00,P155-00-00_0005,6298.5
     840    1199    1370    1928
River Rch & RM=P155-00-00,P155-00-00_0005,5602.1
     854    1218    1393    1959
River Rch & RM=P155-00-00,P155-00-00_0005,5465.6
     945    1347    1542    2161
River Rch & RM=P155-00-00,P155-00-00_0005,4618.7
    1016    1448    1658    2318
River Rch & RM=P155-00-00,P155-00-00_0005,4013.9
    1028    1465    1677    2344
River Rch & RM=P155-00-00,P155-00-00_0005,3917
    1439    2054    2357    3265
River Rch & RM=P155-00-00,P155-00-00_0005,3147.1
    1505    2177    2503    3452
River Rch & RM=P155-00-00,P155-00-00_0005,2443.1
    1549    2261    2604    3579
River Rch & RM=P155-00-00,P155-00-00_0005,1720
    1570    2301    2651    3639
River Rch & RM=P155-00-00,P155-00-00_0005,1390.9
    1588    2335    2692    3691
River Rch & RM=P155-00-00,P155-00-00_0005,1141.6
    1609    2376    2740    3751
River Rch & RM=P155-00-00,P155-00-00_0005,840.2
    1627    2410    2781    3802
Boundary for River Rch & Prof#=P155-00-00,P155-00-00_0005, 1
Up Type= 0
Dn Type= 3
Dn Slope= 0.00130
Boundary for River Rch & Prof#=P155-00-00,P155-00-00_0005, 2
Up Type= 0
Dn Type= 3
Dn Slope= 0.00130
Boundary for River Rch & Prof#=P155-00-00,P155-00-00_0005, 3
Up Type= 0
Dn Type= 3
Dn Slope= 0.00130
Boundary for River Rch & Prof#=P155-00-00,P155-00-00_0005, 4
Up Type= 0
Dn Type= 3
Dn Slope= 0.00130

--- P155-00-00.g01 (geometry) ---

Geom Title=P155-00-00 June 2007
Version=Version 3.0.1  Mar 2001

River Reach=P155-00-00      ,P155-00-00_0005
Reach XY= 30
      3117359.08     13916311.08      3117371.87     13916151.49
      3117371.75       13915904.      3117404.25       13915462.
        3117421.       13915417.      3117463.75       13915387.
       3117520.5       13915381.        3118039.       13915409.
      3118075.75       13915395.        3118114.       13915358.
      3118129.25       13915317.      3118140.52      13915234.2
       3118180.8      13914240.7      3118237.99     13913265.58
      3118269.75       13912439.      3118260.75       13912371.
      3118242.25       13912318.        3118210.       13912267.
        3118155.       13912207.      3118096.75       13912158.
      3118020.75       13912125.        3117883.       13912114.
      3117751.25       13912114.      3117559.75       13912097.
       3117458.5       13912054.      3117375.75       13911982.
        3117319.       13911909.      3117119.75       13911527.
      3117115.25       13911487.      3117140.75       13911002.

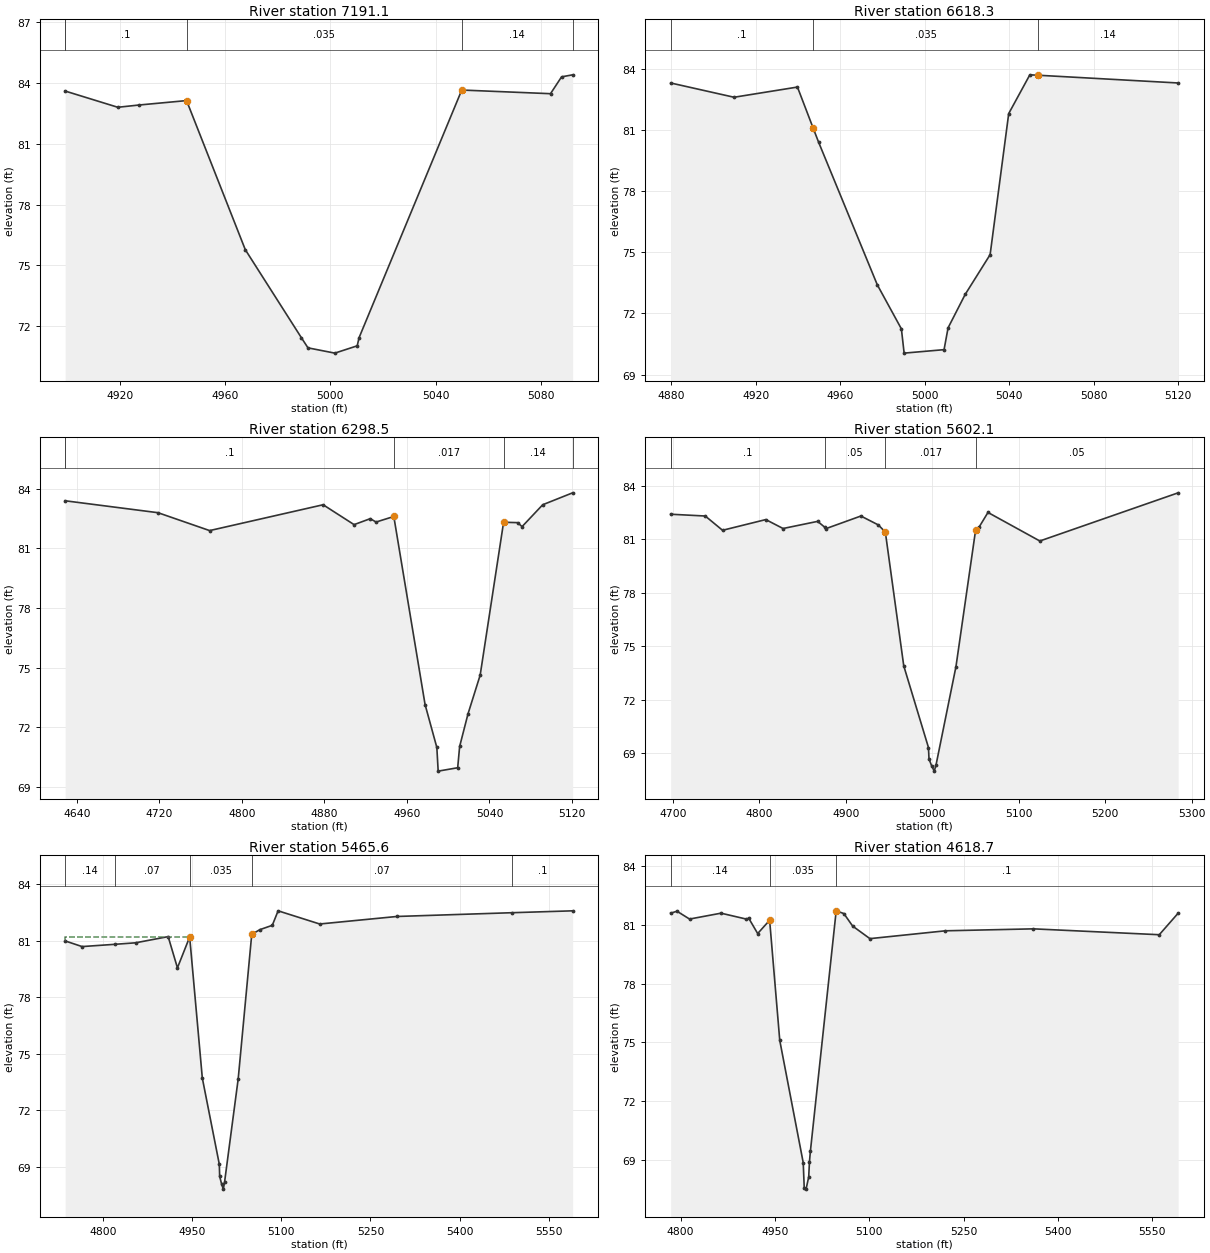
Type RM Length L Ch R = 1 ,7191.1  ,575.1,572.8,568.5
BEGIN DESCRIPTION:
Cross Section 7191.1
END DESCRIPTION:
XS GIS Cut Line= 3
      3117459.09     13916323.11      3117361.31     13916311.26
      3117267.47     13916303.36
#Sta/Elev= 14
  4899.3    83.6  4919.3    82.8  4927.2   82.91  4945.4   83.13  4967.7   75.78
    4989   71.44  4991.5   70.94  5001.7   70.68  5010.2   71.04  5010.9   71.44
  5049.9   83.65  5083.6   83.47  5087.8    84.3    5092    84.4
#Mann= 5 , 1 , 0
  4899.3      .2       0  4899.3      .1       0  4945.4    .035       0
  5049.9     .14       0    5092      .2       0
Bank Sta=4945.4,5049.9
XS Rating Curve= 0
Exp/Cntr=.3,.1

Type RM Length L Ch R = 1 ,6618.3  ,306.9,319.8,337.2
BEGIN DESCRIPTION:
Cross Section 6618.3
END DESCRIPTION:
XS GIS Cut Line= 2
      3117503.82     13915746.93      3117264.11      13915731.6
#Sta/Elev= 16
  4879.8    83.3  4909.8    82.6  4939.8    83.1  4947.3   81.07  4949.8    80.4
  4977.6    73.4    4989   71.24  4990.3   70.05  5009.2   70.22  5011.1   71.29
  5019.2   72.93    5031   74.88  5039.8    81.8  5049.8    83.7  5053.7   83.68
    5120    83.3
#Mann= 3 , 1 , 0
  4879.8      .1       0  4947.3    .035       0  5053.7     .14       0
Bank Sta=4947.3,5053.7
XS Rating Curve= 0
Exp/Cntr=.3,.1

Type RM Length L Ch R = 1 ,6298.5  ,682.5,696.4,660.9
BEGIN DESCRIPTION:
Cross Section 6298.5-Interpolated
END DESCRIPTION:
XS GIS Cut Line= 4
      3117746.32     13915597.33      3117487.22       13915455.
      3117363.12      13915396.6      3117308.32     13915374.68
#Sta/Elev= 20
  4628.8    83.4  4718.8    82.8  4768.8    81.9  4878.8    83.2  4908.8    82.2
  4924.5    82.5  4930.1   82.33  4947.3   82.61  4977.6   73.15    4989   70.99
  4990.3    69.8  5009.2   69.97  5011.1   71.04  5019.2   72.68    5031   74.63
  5053.7   82.32  5067.3    82.3  5071.6    82.1  5091.6    83.2  5120.6    83.8
#Mann= 5 , 1 , 0
  4628.8      .2       0  4628.8      .1       0  4947.3    .017       0
  5053.7     .14       0  5120.6      .2       0
Bank Sta=4947.3,5053.7
XS Rating Curve= 0
Exp/Cntr=.3,.1

Type RM Length L Ch R = 1 ,5602.1  ,168.9,136.5,110.5
BEGIN DESCRIPTION:
Cross Section 5602.1-Interpolated
END DESCRIPTION:
XS GIS Cut Line= 4
      3118333.98     13915560.83      3118140.55      13915418.5
      3118049.31      13915345.5      3117828.82     13915280.04
#Sta/Elev= 23
  4697.4    82.4  4737.4    82.3  4757.4    81.5  4807.4    82.1  4827.4    81.6
  4867.4      82  4875.4   81.68  4877.4    81.6  4917.4    82.3  4937.6    81.8
  4945.7    81.4    4967    73.9  4995.6   69.32  4996.2   68.68  4999.4   68.28
  5002.3      68  5004.4   68.36  5027.4   73.86  5050.2   81.54  5054.4    81.7
  5064.4    82.5  5124.4    80.9  5284.4    83.6
#Mann= 5 , 1 , 0
  4697.4      .2       0  4697.4      .1       0  4875.4     .05       0
  4945.7    .017       0  5050.2     .05       0
Bank Sta=4945.7,5050.2
XS Rating Curve= 0
Exp/Cntr=.3,.1

Type RM Length L Ch R = 1 ,5465.6  ,843.9,846.9,851.8
BEGIN DESCRIPTION:
Cross Section 5465.6
END DESCRIPTION:
XS GIS Cut Line= 4
      3118401.12     13915262.68      3118372.99     13915258.18
      3117797.21     13915252.18      3117547.29     13915245.93
#Sta/Elev= 22
  4736.1      81  4764.6    80.7  4819.5   80.82  4854.6    80.9  4909.5   81.23
  4925.1   79.57  4945.7   81.21    4967   73.71  4995.6   69.13  4996.2   68.49
  4999.4   68.09  5002.3   67.81  5004.4   68.17  5027.4   73.67  5050.2   81.35
  5063.9    81.6  5084.8   81.83  5094.6    82.6  5164.6    81.9  5294.6    82.3
  5488.5    82.5  5590.4    82.6
#Mann= 5 , 1 , 0
  4736.1     .14       0  4819.5     .07       0  4945.7    .035       0
  5050.2     .07       0  5488.5      .1       0
#XS Ineff= 2 , 0
       0  4945.7   81.21               0
Permanent Ineff=
       F       F
Bank Sta=4945.7,5050.2
XS Rating Curve= 0
Exp/Cntr=.3,.1

Type RM Length L Ch R = 1 ,4618.7  ,609.1,604.8,602.7
BEGIN DESCRIPTION:
Cross Section 4618.7
END DESCRIPTION:
XS GIS Cut Line= 3
      3118389.44     13914419.18      3118103.09     13914406.52
      3117584.09     13914373.09
#Sta/Elev= 23
  4784.3    81.6  4794.3    81.7  4814.3    81.3  4864.3    81.6  4904.3    81.3
  4908.4   81.34  4922.6   80.56  4941.6   81.24  4957.7    75.1    4995   68.86
  4996.6   67.57  4999.5   67.51  5003.7   68.13  5004.9    68.9  5006.4   69.45
  5047.4   81.72  5059.6   81.58  5073.6   80.94    5101    80.3    5221    80.7
    5361    80.8    5561    80.5    5591    81.6
#Mann= 3 , 1 , 0
  4784.3     .14       0  4941.6    .035       0  5047.4      .1       0
Bank Sta=4941.6,5047.4
XS Rating Curve= 0
Exp/Cntr=.3,.1

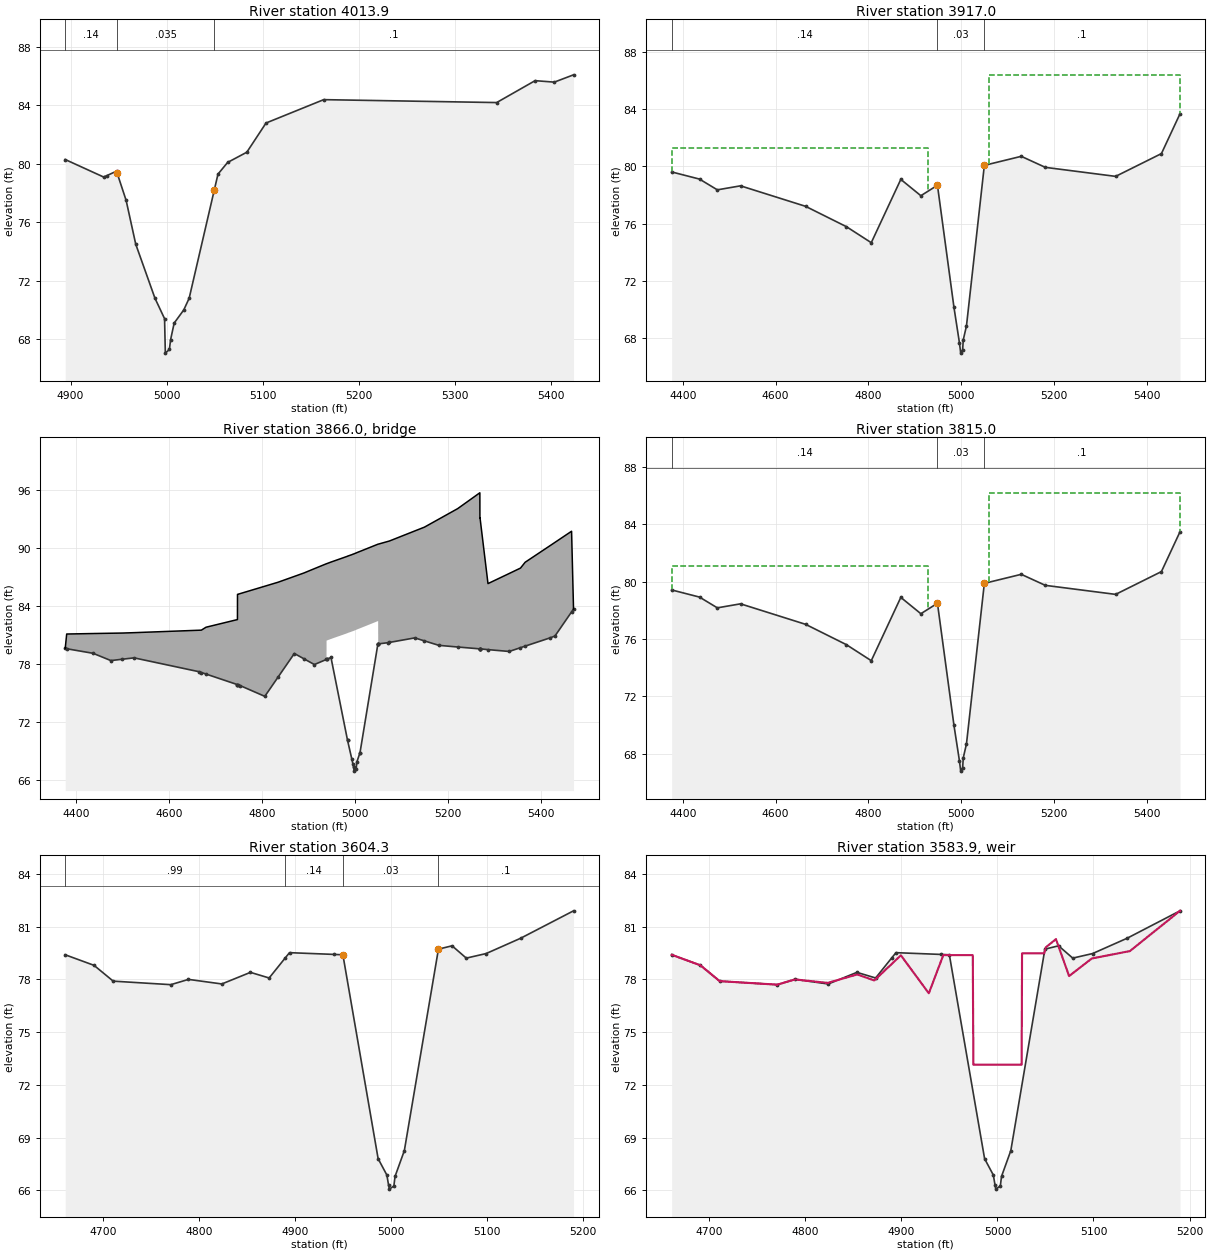
Type RM Length L Ch R = 1 ,4013.9  ,100.8,96.9,95.7
BEGIN DESCRIPTION:
Cross Section 4013.9-Interpolated
END DESCRIPTION:
XS GIS Cut Line= 4
      3118309.31     13913803.61      3118265.86     13913803.61
      3118180.34     13913806.36      3117780.41     13913800.15
#Sta/Elev= 25
  4894.4    80.3  4934.4    79.1  4937.8    79.2  4947.8    79.5  4948.5   79.36
  4957.8    77.5  4967.8    74.5  4987.8    70.8  4997.8    69.4  4998.6   67.04
  5002.8   67.29  5004.1   67.97  5007.8    69.1  5017.8      70  5023.4    70.8
  5049.5    78.2  5053.4    79.3  5063.4    80.1  5083.4    80.8  5103.4    82.8
  5163.4    84.4  5343.4    84.2  5383.4    85.7  5403.4    85.6  5423.4    86.1
#Mann= 3 , 1 , 0
  4894.4     .14       0  4948.5    .035       0  5049.5      .1       0
Bank Sta=4948.5,5049.5
XS Rating Curve= 0
Exp/Cntr=.5,.3

Type RM Length L Ch R = 1 ,3917.0  ,102,102,102
BEGIN DESCRIPTION:
Upstream Section of Bridge/Culvert/Weir
END DESCRIPTION:
XS GIS Cut Line= 6
      3118832.42     13913628.75      3118663.21     13913633.47
       3118286.9     13913675.61      3118176.34     13913678.96
      3117925.06     13913695.71      3117740.93     13913690.59
#Sta/Elev= 22
  4376.2   79.62  4436.2   79.12  4474.5   78.37  4524.5   78.65  4664.5   77.22
  4752.4    75.8    4806   74.68  4869.6    79.1  4912.8   77.96  4948.5   78.69
  4984.1   70.16  4995.8    67.7  4998.6   66.97  5002.8   67.22  5004.1    67.9
    5011   68.87  5049.5   80.08    5129   80.71  5180.8   79.94  5332.2   79.31
  5430.8    80.9  5470.8   83.68
#Mann= 3 , 1 , 0
  4376.2     .14       0  4948.5     .03       0  5049.5      .1       0
#XS Ineff= 2 , 0
       0    4928    81.3    5060       0    86.4
Permanent Ineff=
       F       F
Bank Sta=4948.5,5049.5
XS Rating Curve= 0
Exp/Cntr=.5,.3

Type RM Length L Ch R = 3 ,3866.0  ,,,
BEGIN DESCRIPTION:
HARDY AIRPORT CONNECTOR
Structure ID: P55-5
END DESCRIPTION:
Bridge Culvert--1,0,-1,-1, 0
Deck Dist Width WeirC Skew NumUp NumDn MinLoCord MaxHiCord MaxSubmerge Is_Ogee
10,82,2.6,0, 55, 55, , , .95, 0, 1,1,,
  4376.2  4379.4  4436.2  4474.5  4499.4  4524.5  4664.5  4669.4  4679.4 4747.09
  4747.2 4747.31  4752.4    4806  4834.5  4869.6    4890  4912.8  4938.8 4938.91
    4939  4948.5  4984.1  4984.2  4993.2  4995.8    4997  4998.6  5002.8  5004.1
  5010.9    5011  5049.5 5050.09  5050.2  5050.4    5072  5074.2    5129  5149.7
  5180.8  5221.3  5268.6 5268.99  5269.1 5269.21  5269.5  5286.6  5332.2  5356.6
  5366.6  5420.8  5430.8  5466.6  5470.8
   79.61    81.1   81.15   81.18    81.2   81.24   81.49    81.5    81.8   82.59
   85.19   85.19   85.26   86.03   86.44   87.04   87.39   87.84   88.35   88.35
   88.35   88.52   89.12   89.13   89.28   89.33   89.35   89.38   89.46   89.49
   89.62   89.62   90.36   90.37   90.37   90.37   90.66   90.69   91.73   92.12
   92.95   94.03   95.65   95.66   95.66   93.06   93.07    86.3   87.34    87.9
    88.5   90.23   90.55    91.7   83.67
   79.61   79.58   79.11   78.36    78.5   78.64   77.21   77.13   76.97   75.88
   75.87   75.87   75.79   74.67   76.65   79.09   78.55   77.95   78.48   78.48
   80.42   80.59   81.19    81.2   81.35    81.4   81.42   81.45   81.53   81.56
   81.69   81.69   82.43   82.44   80.07   80.08   80.21   80.23    80.7   80.39
   79.93   79.76   79.57   79.57   79.57   79.57   79.57   79.49    79.3   79.69
   79.85   80.71   80.89   83.38   83.67
  4376.2  4379.4  4436.2  4474.5  4499.4  4524.5  4664.5  4669.4  4679.4 4747.09
  4747.2 4747.31  4752.4    4806  4834.5  4869.6    4890  4912.8  4938.8 4938.91
    4939  4948.5  4984.1  4984.2  4993.2  4995.8    4997  4998.6  5002.8  5004.1
  5010.9    5011  5049.5 5050.09  5050.2  5050.4    5072  5074.2    5129  5149.7
  5180.8  5221.3  5268.6 5268.99  5269.1 5269.21  5269.5  5286.6  5332.2  5356.6
  5366.6  5420.8  5430.8  5466.6  5470.8
   79.61    81.1   81.15   81.18    81.2   81.24   81.49    81.5    81.8   82.59
   85.19   85.19   85.26   86.03   86.44   87.04   87.39   87.84   88.35   88.35
   88.35   88.52   89.12   89.13   89.28   89.33   89.35   89.38   89.46   89.49
   89.62   89.62   90.36   90.37   90.37   90.37   90.66   90.69   91.73   92.12
   92.95   94.03   95.65   95.66   95.66   93.06   93.07    86.3   87.34    87.9
    88.5   90.23   90.55    91.7   83.67
   79.45   79.42   78.95    78.2   78.34   78.48   77.05   76.97   76.81   75.72
   75.71   75.71   75.63   74.51   76.49   78.93   78.39   77.79   78.32   78.32
   80.26   80.43   81.03   81.04   81.19   81.24   81.26   81.29   81.37    81.4
   81.53   81.53   82.27   82.28   79.91   79.92   80.05   80.07   80.54   80.23
   79.77    79.6   79.41   79.41   79.41   79.41   79.41   79.33   79.14   79.53
   79.69   80.55   80.73   83.22   83.51
Abutment Skew #Up #Dn= , 2 , 2
  4938.8  4984.2
   80.42   70.13
  4938.8  4984.2
   80.26   69.97
Abutment Skew #Up #Dn= , 2 , 2
    5011 5050.29
   68.86   82.44
    5011 5050.29
    68.7   82.28
BR Coef= 1 , 1 , 0 ,1.25, 0 ,,,.8,0,2,0,
WSPro=,,,, 1 ,,,, 0 ,,,, 0 ,,,,-1 ,-1 ,-1 , 0 , 0 , 0 , 0 , 0
BR U #Sta/Elev= 55
  4376.2   79.61  4379.4   79.58  4436.2   79.11  4474.5   78.36  4499.4    78.5
  4524.5   78.64  4664.5   77.21  4669.4   77.13  4679.4   76.97 4747.09   75.88
  4747.2   75.87 4747.31   75.87  4752.4   75.79    4806   74.67  4834.5   76.65
  4869.6   79.09    4890   78.55  4912.8   77.95  4938.8   78.48 4938.91   78.48
    4939   78.49  4948.5   78.68  4984.1   70.15  4984.2   70.13  4993.2   68.24
  4995.8   67.69    4997   67.37  4998.6   66.96  5002.8   67.21  5004.1   67.89
  5010.9   68.85    5011   68.86  5049.5   80.07 5050.09   80.07  5050.2   80.07
  5050.4   80.08    5072   80.21  5074.2   80.23    5129    80.7  5149.7   80.39
  5180.8   79.93  5221.3   79.76  5268.6   79.57 5268.99   79.57  5269.1   79.57
 5269.21   79.57  5269.5   79.57  5286.6   79.49  5332.2    79.3  5356.6   79.69
  5366.6   79.85  5420.8   80.71  5430.8   80.89  5466.6   83.38  5470.8   83.67
BR U #Mann= 3
  4376.2     .14  4948.5     .03  5049.5      .1
BR U Banks=4948.5,5049.5
BR D #Sta/Elev= 55
  4376.2   79.45  4379.4   79.42  4436.2   78.95  4474.5    78.2  4499.4   78.34
  4524.5   78.48  4664.5   77.05  4669.4   76.97  4679.4   76.81 4747.09   75.72
  4747.2   75.71 4747.31   75.71  4752.4   75.63    4806   74.51  4834.5   76.49
  4869.6   78.93    4890   78.39  4912.8   77.79  4938.8   78.32 4938.91   78.32
    4939   78.33  4948.5   78.52  4984.1   69.99  4984.2   69.97  4993.2   68.08
  4995.8   67.53    4997   67.21  4998.6    66.8  5002.8   67.05  5004.1   67.73
  5010.9   68.69    5011    68.7  5049.5   79.91 5050.09   79.91  5050.2   79.91
  5050.4   79.92    5072   80.05  5074.2   80.07    5129   80.54  5149.7   80.23
  5180.8   79.77  5221.3    79.6  5268.6   79.41 5268.99   79.41  5269.1   79.41
 5269.21   79.41  5269.5   79.41  5286.6   79.33  5332.2   79.14  5356.6   79.53
  5366.6   79.69  5420.8   80.55  5430.8   80.73  5466.6   83.22  5470.8   83.51
BR D #Mann= 3
  4376.2     .14  4948.5     .03  5049.5      .1
BR D Banks=4948.5,5049.5
BC Design=,, 0 ,, 0 ,,,,,,

Type RM Length L Ch R = 1 ,3815.0  ,210.7,210.7,210.7
BEGIN DESCRIPTION:
Downstream Section of Bridge/Culvert/Weir
END DESCRIPTION:
XS GIS Cut Line= 6
      3118838.27     13913526.92      3118669.07     13913531.63
      3118292.76     13913573.77       3118182.2     13913577.12
      3117930.92     13913593.87      3117746.78     13913588.76
#Sta/Elev= 22
  4376.2   79.42  4436.2   78.92  4474.5   78.17  4524.5   78.45  4664.5   77.02
  4752.4    75.6    4806   74.48  4869.6    78.9  4912.8   77.76  4948.5   78.49
  4984.1   69.96  4995.8    67.5  4998.6   66.77  5002.8   67.02  5004.1    67.7
    5011   68.67  5049.5   79.88    5129   80.51  5180.8   79.74  5332.2   79.11
  5430.8    80.7  5470.8   83.48
#Mann= 3 , 1 , 0
  4376.2     .14       0  4948.5     .03       0  5049.5      .1       0
#XS Ineff= 2 , 0
       0    4928    81.1    5060       0    86.2
Permanent Ineff=
       F       F
Bank Sta=4948.5,5049.5
XS Rating Curve= 0
Exp/Cntr=.5,.3

Type RM Length L Ch R = 1 ,3604.3  ,38.5,38.5,38.5
BEGIN DESCRIPTION:
Cross Section 3604.3, Upstream Section of Weir
END DESCRIPTION:
XS GIS Cut Line= 2
      3118570.22     13913381.13      3118041.53     13913353.61
#Sta/Elev= 25
  4660.7    79.4  4690.7    78.8  4710.7    77.9  4770.7    77.7  4789.1      78
  4823.8   77.74  4853.6    78.4  4873.1   78.08  4889.7   79.21  4894.3   79.52
    4941   79.42  4949.9    79.4  4986.6    67.8  4995.7   66.87  4997.5   66.29
  4998.3   66.07    5003   66.25  5004.2   66.79  5013.9   68.26  5049.4   79.72
  5063.6   79.91  5078.4   79.21  5099.1   79.47    5135   80.34  5190.1    81.9
#Mann= 4 , 1 , 0
  4660.7     .99       0  4889.7     .14       0  4949.9     .03       0
  5049.4      .1       0
#XS Ineff= 2 , 0
       0                  5063.6       0   79.91
Permanent Ineff=
       F       F
Bank Sta=4949.9,5049.4
XS Rating Curve= 0
Exp/Cntr=.7,.5

Type RM Length L Ch R = 5 ,3583.9  ,,,
BEGIN DESCRIPTION:
SHEET PILE WEIR
Structure ID:
END DESCRIPTION:
IW Pilot Flow=0
#Inline Weir SE= 22
  4660.7    79.4  4690.7    78.8  4710.7    77.9  4770.7    77.7  4789.1      78
  4823.1    77.8    4854   78.28  4871.7   77.94  4899.4   79.37  4928.5   77.21
  4943.6   79.38  4974.3   79.38  4974.9   73.15  5025.2   73.15  5025.6   79.48
  5048.7   79.48  5050.3   79.82  5060.9   80.29  5074.6   78.19  5098.3   79.19
  5137.9   79.61  5190.1    81.9
IW Dist,WD,Coef,Skew,MaxSub,Min_El,Is_Ogee,SpillHt,DesHd
10,1,3,0,.95,, 0 ,,,1,1,

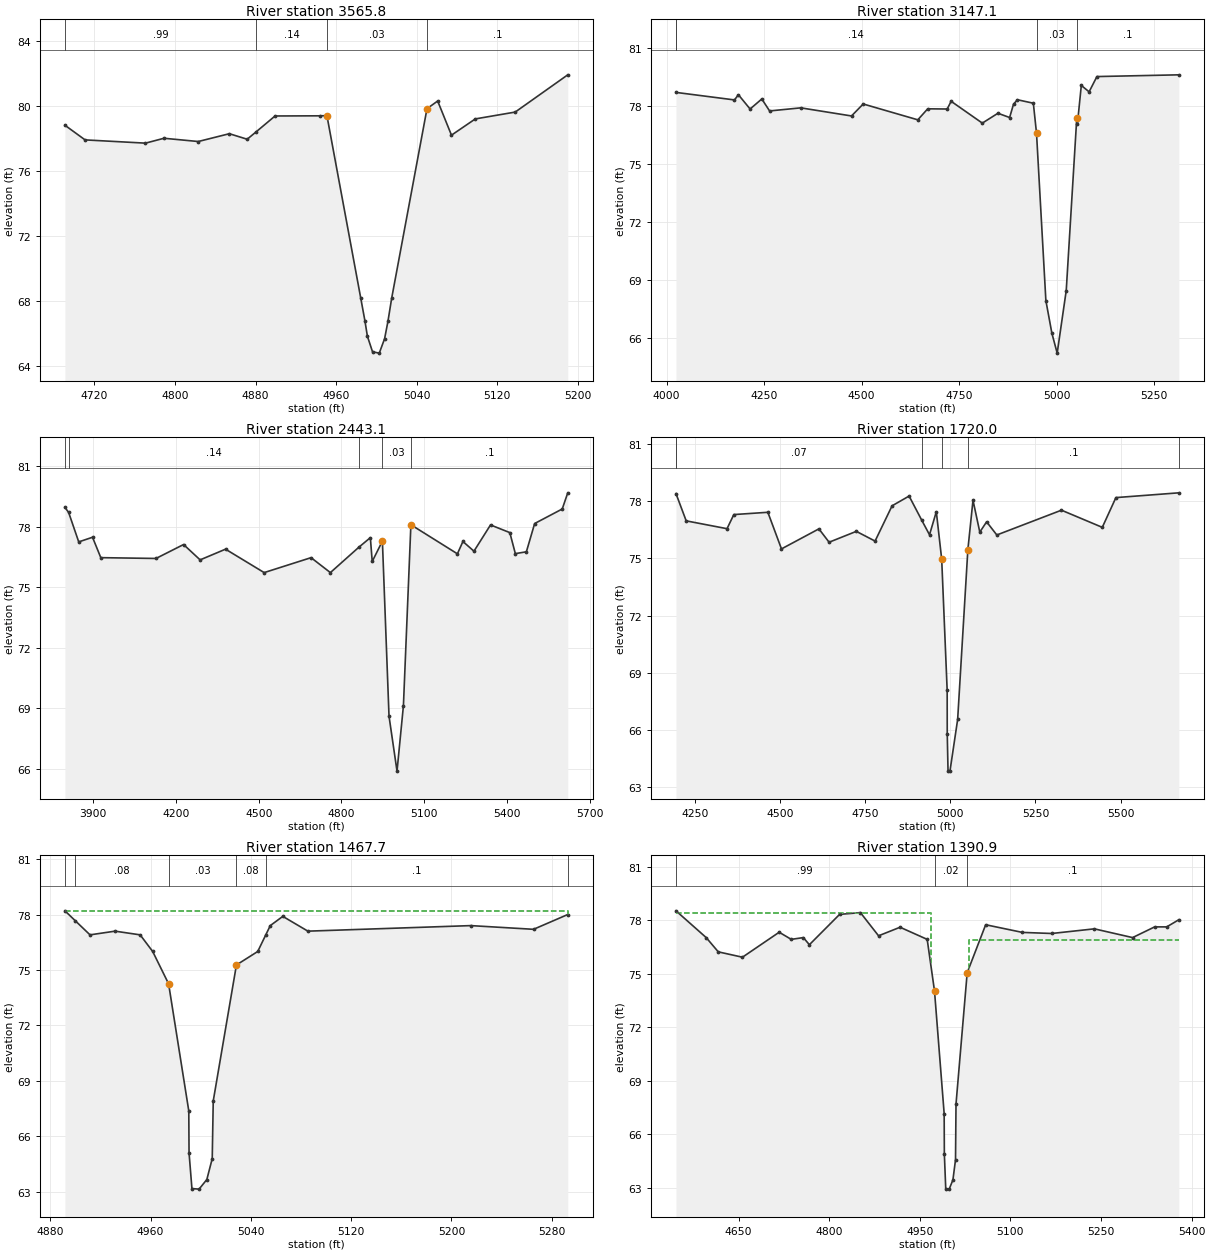
Type RM Length L Ch R = 1 ,3565.8  ,418.7,418.7,418.7
BEGIN DESCRIPTION:
Cross Section 3565.8, Downstream Section of Weir
END DESCRIPTION:
XS GIS Cut Line= 2
      3118542.77     13913342.66      3118044.18     13913314.27
#Sta/Elev= 25
  4690.7    78.8  4710.7    77.9  4770.7    77.7  4789.1      78  4823.1    77.8
    4854   78.28  4871.7   77.94  4880.7    78.4  4899.4   79.37  4943.6   79.38
  4950.9   79.39  4984.5   68.17  4988.6   66.79  4991.1   65.83  4996.2   64.87
  5002.9   64.79  5008.2   65.68  5011.5   66.74  5015.2   68.16  5050.3   79.82
  5060.9   80.29  5074.6   78.19  5098.3   79.19  5137.9   79.61  5190.1    81.9
#Mann= 4 , 1 , 0
  4690.7     .99       0  4880.7     .14       0  4950.9     .03       0
  5050.3      .1       0
#XS Ineff= 2 , 0
       0                  5060.9       0   80.29
Permanent Ineff=
       F       F
Bank Sta=4950.9,5050.3
XS Rating Curve= 0
Exp/Cntr=.7,.5

Type RM Length L Ch R = 1 ,3147.1  ,737.7,704,667.8
BEGIN DESCRIPTION:
Cross Section 3147.1-Interpolated
END DESCRIPTION:
XS GIS Cut Line= 5
      3119223.17     13913022.96      3118602.83     13912943.17
       3118312.1      13912940.2       3118239.1      13912940.2
      3117939.22     13912930.73
#Sta/Elev= 30
    4024    78.7    4174   78.31    4184   78.58    4214   77.84    4244   78.36
    4264   77.74    4344    77.9    4474   77.48    4504    78.1    4644   77.28
  4669.4   77.85  4719.4   77.84  4729.4   78.24  4809.4   77.11  4849.4   77.62
  4879.4    77.4  4889.4   78.09  4899.4   78.32  4940.2   78.14 4948.35   76.59
 4972.35   67.92 4987.75   66.23 5001.35    65.2 5024.55   68.44 5051.65    77.4
  5053.2   77.07  5063.2   79.06  5083.2   78.73  5103.2   79.52  5313.2   79.61
#Mann= 4 , 1 , 0
    4024      .2       0    4024     .14       0 4948.35     .03       0
 5051.65      .1       0
#XS Ineff= 2 , 0
       0  4899.4    77.5               0
Permanent Ineff=
       F       F
Bank Sta=4948.35,5051.65
XS Rating Curve= 0
Exp/Cntr=.3,.1

Type RM Length L Ch R = 1 ,2443.1  ,736.8,723.1,696.1
BEGIN DESCRIPTION:
Cross Section 2443.1
END DESCRIPTION:
XS GIS Cut Line= 5
      3119308.45     13912171.18      3118754.58      13911992.2
      3118293.96     13912173.38      3118075.93     13912357.62
       3117765.7     13912697.27
#Sta/Elev= 30
  3797.7   78.95  3811.1    78.7  3847.7   77.24  3897.7   77.47  3927.7   76.46
  4127.7   76.42  4227.7   77.11  4287.7   76.35  4379.8   76.88  4519.8   75.72
  4689.8   76.46  4759.8   75.72  4863.3   76.98  4904.7   77.45 4911.45   76.27
 4948.35   77.28 4972.35   68.61 5001.35   65.89 5024.55   69.13 5051.65   78.09
  5220.2   76.65  5240.2   77.26  5280.2   76.78  5340.2   78.08  5410.2    77.7
  5430.2   76.66  5470.2   76.75  5500.2   78.15  5600.2   78.87  5620.2   79.67
#Mann= 5 , 1 , 0
  3797.7      .1       0  3811.1     .14       0  4863.3      .1       0
 4948.35     .03       0 5051.65      .1       0
#XS Ineff= 2 , 0
       0  4904.7    77.3  5104.7       0    77.3
Permanent Ineff=
       F       F
Bank Sta=4948.35,5051.65
XS Rating Curve= 0
Exp/Cntr=.3,.1

Type RM Length L Ch R = 1 ,1720.0  ,247.9,252.3,343.3
BEGIN DESCRIPTION:
Cross Section 1720.0-Interpolaed
END DESCRIPTION:
XS GIS Cut Line= 5
      3118118.59     13911605.66      3117605.44     13911865.26
      3117538.32     13912045.97      3117501.82     13912144.52
       3117301.5     13912715.29
#Sta/Elev= 30
  4193.5    78.4  4223.5   76.97  4343.5   76.56  4363.5    77.3  4463.5   77.42
  4503.5    75.5  4613.5   76.55  4643.5   75.85  4723.5   76.42  4778.6   75.91
  4828.6   77.76  4878.6   78.27  4915.9      77  4938.6   76.24  4958.6   77.45
  4974.4   74.96  4990.5   68.08  4990.7   65.82    4993   63.88  4998.7   63.85
  5021.3   66.56  5051.3   75.46  5066.4   78.05  5086.4   76.38  5106.4   76.92
  5136.4   76.23  5326.4   77.53  5446.4   76.63  5486.4   78.19  5671.3   78.44
#Mann= 6 , 1 , 0
  4193.5      .2       0  4193.5     .07       0  4915.9      .1       0
  4974.4     .03       0  5051.3      .1       0  5671.3      .2       0
#XS Ineff= 2 , 0
       0  4828.6      77  5066.4       0      77
Permanent Ineff=
       F       F
Bank Sta=4974.4,5051.3
XS Rating Curve= 0
Exp/Cntr=.3,.1

Type RM Length L Ch R = 1 ,1467.7  ,69.4,76.8,79
BEGIN DESCRIPTION:
Cross Section 1467.7-Interpolated
END DESCRIPTION:
XS GIS Cut Line= 4
       3117396.8     13911823.76      3117325.73     13911861.26
       3117264.3     13911901.51      3117044.01     13912013.77
#Sta/Elev= 23
  4891.7    78.2    4900   77.66  4911.7    76.9  4931.7    77.1  4951.7    76.9
  4961.7      76  4974.4   74.25  4990.5   67.37  4990.7   65.11    4993   63.17
  4998.7   63.14  5004.9   63.66  5009.2   64.79    5010   67.91  5028.5   75.27
  5045.5      76  5051.7   76.87  5055.5    77.4  5065.5    77.9  5085.5    77.1
  5215.5    77.4  5265.5    77.2  5292.8      78
#Mann= 6 , 1 , 0
  4891.7     .07       0    4900     .08       0  4974.4     .03       0
  5028.5     .08       0  5051.7      .1       0  5292.8      .2       0
#XS Ineff= 2 , 0
       0  4891.7    78.2               0
Permanent Ineff=
       F       F
Bank Sta=4974.4,5028.5
XS Rating Curve= 0
Exp/Cntr=.5,.3

Type RM Length L Ch R = 1 ,1390.9  ,132.6,132.6,132.6
BEGIN DESCRIPTION:
Upstream Section of Bridge/Culvert/Weir
END DESCRIPTION:
XS GIS Cut Line= 6
      3117676.22     13911612.18      3117444.18     13911738.74
      3117371.18     13911779.69      3117278.59     13911829.55
      3117189.57     13911872.28      3116930.99     13911980.66
#Sta/Elev= 30
  4546.5   78.53  4596.5   77.03  4616.5   76.23  4656.5   75.93  4717.3   77.33
  4737.3   76.93  4757.3   77.03  4767.3   76.63  4817.3   78.33  4851.8   78.43
  4881.8   77.13  4917.4   77.61  4962.3   76.93  4974.4   74.04  4990.4   67.16
  4990.7    64.9    4993   62.96  4998.7   62.93  5004.9   63.45  5009.2   64.58
    5010    67.7  5028.5   75.06  5059.1   77.75    5120   77.32  5168.5   77.26
    5239   77.52  5302.3   77.03  5338.8   77.63  5358.8   77.63  5378.8   78.03
#Mann= 3 , 1 , 0
  4546.5     .99       0  4974.4     .02       0  5028.5      .1       0
#XS Ineff= 2 , 0
       0    4968    78.4    5031       0    76.9
Permanent Ineff=
       F       F
Bank Sta=4974.4,5028.5
XS Rating Curve= 0
Exp/Cntr=.5,.3