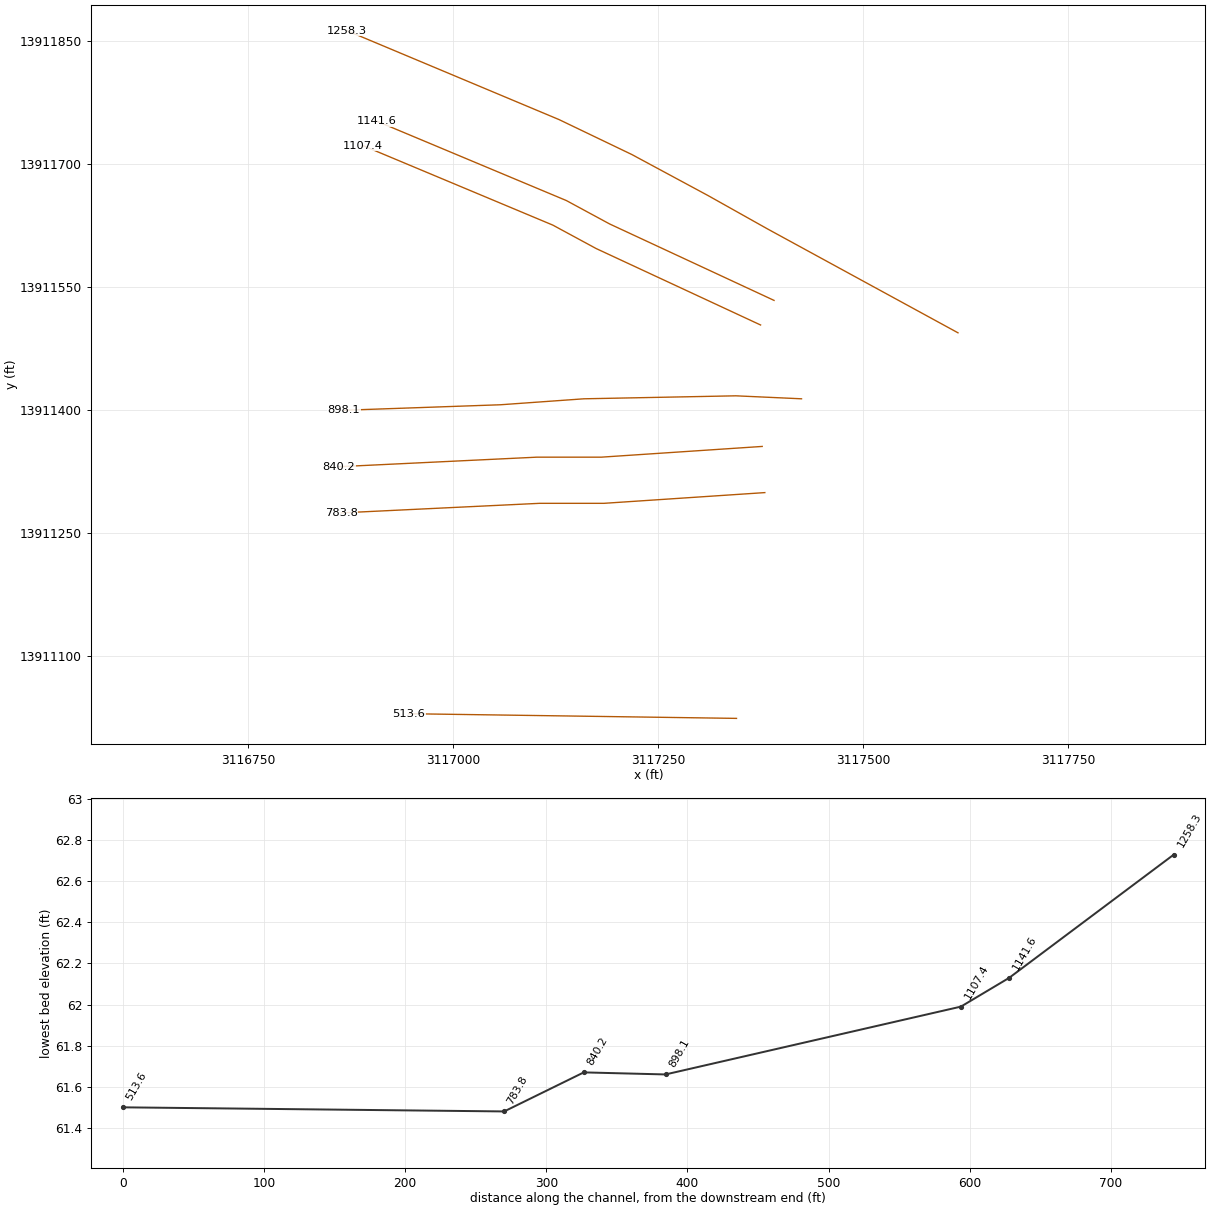
HEC-RAS study P155-00-00.PRJ: P155-00-00

--- P155-00-00.g01 (geometry) --- (continued)

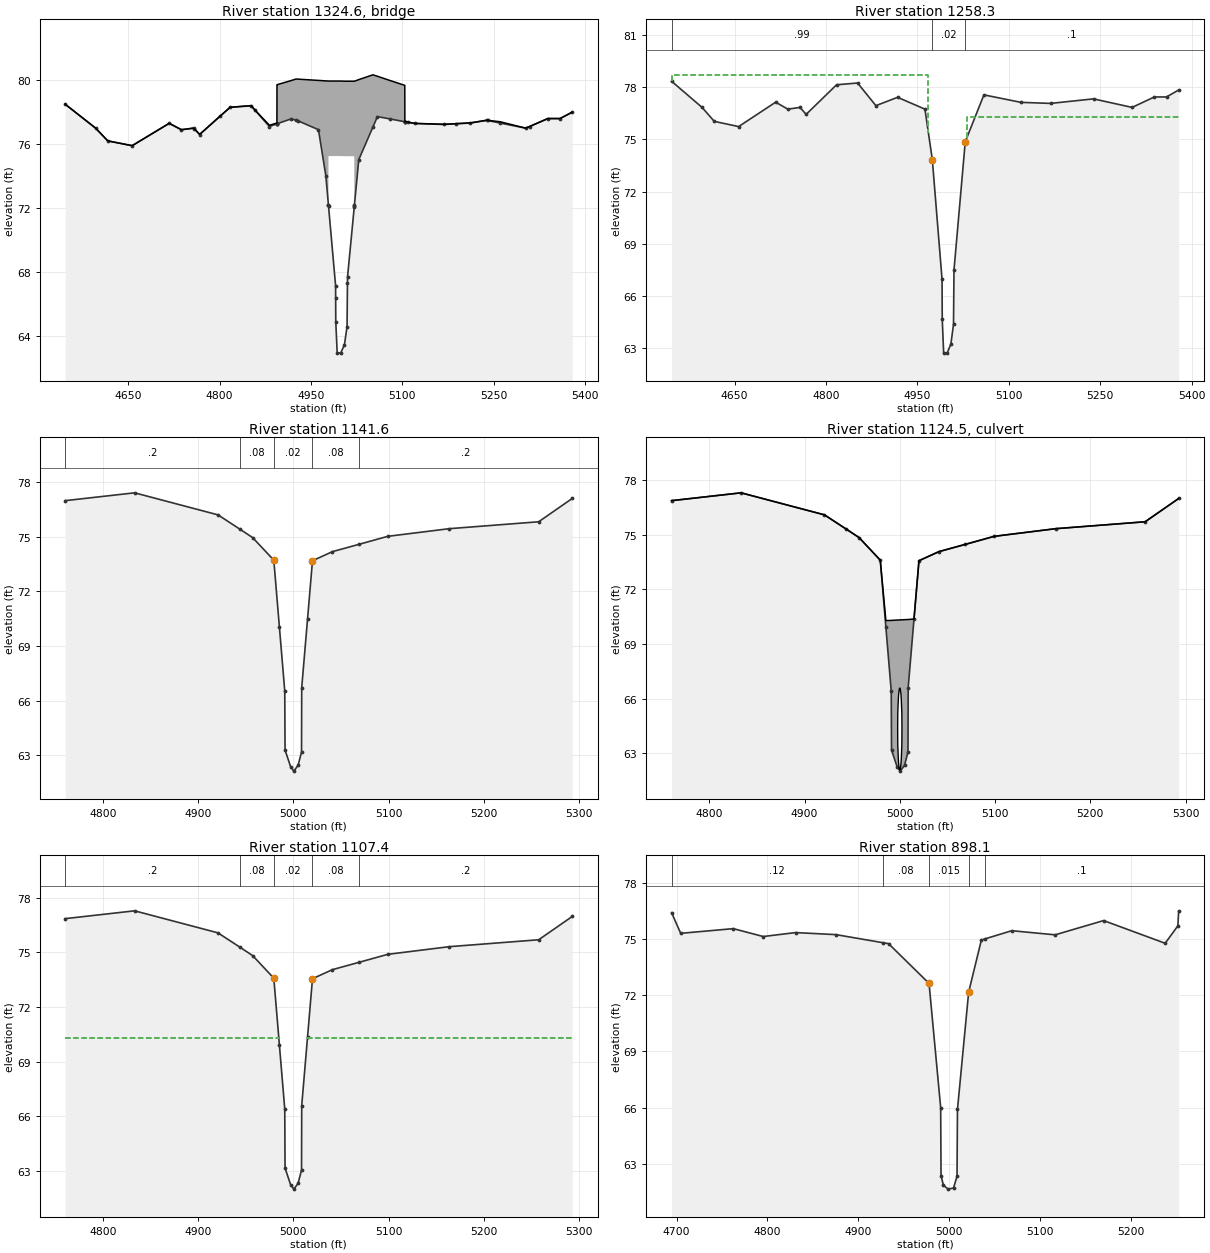
Type RM Length L Ch R = 3 ,1324.6  ,,,
BEGIN DESCRIPTION:
GREENS ROAD
Structure ID: P55-3
END DESCRIPTION:
Bridge Culvert--1,0,-1,-1, 0
Deck Dist Width WeirC Skew NumUp NumDn MinLoCord MaxHiCord MaxSubmerge Is_Ogee
10,112.6,2.6,0, 57, 57, , , .95, 0, 1,1,,
  4546.5  4596.5  4616.5  4656.5  4717.3  4737.3  4757.3  4758.8  4767.3  4800.7
  4817.3  4851.8  4858.2  4881.8 4894.09  4894.2 4894.31  4917.4  4925.7  4928.5
  4962.3  4974.4 4978.61  4978.7  4978.8  4990.4  4990.5  4990.7    4993  4998.7
  5004.9  5009.2  5009.9    5010 5021.09  5021.2  5021.3  5028.5  5051.6  5059.1
  5079.3 5103.89    5104 5104.11  5109.1    5120  5168.5  5187.7  5211.8    5239
  5239.9  5260.4  5302.3  5308.8  5338.8  5358.8  5378.8
    78.5      77    76.2    75.9    77.3    76.9      77   76.95   76.61   77.75
   78.31   78.41   78.13   77.18   77.32   79.72   79.72   79.98   80.08   80.07
   79.99   79.96   79.95   79.95   79.95   79.95   79.95   79.95   79.95   79.95
   79.94   79.94   79.94   79.94   79.94   79.94   79.94   80.04   80.34   80.25
   79.99   79.68   79.68   77.41   77.38    77.3   77.24   77.28   77.33    77.5
   77.49    77.4      77    77.1    77.6    77.6      78
    78.5      77    76.2    75.9    77.3    76.9      77   76.94    76.6   77.74
    78.3    78.4   78.12    77.1   77.27   77.27   77.27   77.58   77.49   77.46
    76.9   74.01    72.2   75.25   75.25   75.25   75.25   75.25   75.25   75.25
   75.24   75.24   75.24   75.24   75.24   72.13   72.17   75.03   77.06   77.72
   77.58    77.4    77.4    77.4   77.37   77.29   77.23   77.27   77.32   77.49
   77.48   77.32      77    77.1    77.6    77.6      78
  4546.5  4596.5  4616.5  4656.5  4717.3  4737.3  4757.3  4758.8  4767.3  4800.7
  4817.3  4851.8  4858.2  4881.8 4894.09  4894.2 4894.31  4917.4  4925.7  4928.5
  4962.3  4974.4 4978.61  4978.7  4978.8  4990.4  4990.5  4990.7    4993  4998.7
  5004.9  5009.2  5009.9    5010 5021.09  5021.2  5021.3  5028.5  5051.6  5059.1
  5079.3 5103.89    5104 5104.11  5109.1    5120  5168.5  5187.7  5211.8    5239
  5239.9  5260.4  5302.3  5308.8  5338.8  5358.8  5378.8
    78.5      77    76.2    75.9    77.3    76.9      77   76.95   76.61   77.75
   78.31   78.41   78.13   77.18   77.32   79.72   79.72   79.98   80.08   80.07
   79.99   79.96   79.95   79.95   79.95   79.95   79.95   79.95   79.95   79.95
   79.94   79.94   79.94   79.94   79.94   79.94   79.94   80.04   80.34   80.25
   79.99   79.68   79.68   77.41   77.38    77.3   77.24   77.28   77.33    77.5
   77.49    77.4      77    77.1    77.6    77.6      78
    78.3    76.8      76    75.7    77.1    76.7    76.8   76.74    76.4   77.54
    78.1    78.2   77.92    76.9   77.07   77.07   77.07   77.38   77.29   77.26
    76.7   73.81      72   75.05   75.05   75.05   75.05   75.05   75.05   75.05
   75.04   75.04   75.04   75.04   75.04   71.93   71.97   74.83   76.86   77.52
   77.38    77.2    77.2    77.2   77.17   77.09   77.03   77.07   77.12   77.29
   77.28   77.12    76.8    76.9    77.4    77.4    77.8
Abutment Skew #Up #Dn= , 2 , 2
  4978.5  4990.5
   75.25   66.38
  4978.5  4990.5
   75.05   66.18
Abutment Skew #Up #Dn= , 2 , 2
    5010 5021.29
   67.67   75.24
    5010 5021.29
   67.47   75.04
BR Coef= 1 , 1 , 0 ,1.25, 0 ,,,.8,0,2,0,
WSPro=,,,, 1 ,,,, 0 ,,,, 0 ,,,,-1 ,-1 ,-1 , 0 , 0 , 0 , 0 , 0
BR U #Sta/Elev= 57
  4546.5    78.5  4596.5      77  4616.5    76.2  4656.5    75.9  4717.3    77.3
  4737.3    76.9  4757.3      77  4758.8   76.94  4767.3    76.6  4800.7   77.74
  4817.3    78.3  4851.8    78.4  4858.2   78.12  4881.8    77.1 4894.09   77.27
  4894.2   77.27 4894.31   77.27  4917.4   77.58  4925.7   77.49  4928.5   77.46
  4962.3    76.9  4974.4   74.01 4978.61    72.2  4978.7   72.16  4978.8   72.12
  4990.4   67.13  4990.5   66.38  4990.7   64.87    4993   62.93  4998.7    62.9
  5004.9   63.42  5009.2   64.55  5009.9   67.28    5010   67.67 5021.09   72.08
  5021.2   72.13  5021.3   72.17  5028.5   75.03  5051.6   77.06  5059.1   77.72
  5079.3   77.58 5103.89    77.4    5104    77.4 5104.11    77.4  5109.1   77.37
    5120   77.29  5168.5   77.23  5187.7   77.27  5211.8   77.32    5239   77.49
  5239.9   77.48  5260.4   77.32  5302.3      77  5308.8    77.1  5338.8    77.6
  5358.8    77.6  5378.8      78
BR U #Mann= 3
  4546.5     .99  4974.4     .02  5028.5      .1
BR U Banks=4974.4,5028.5
BR D #Sta/Elev= 57
  4546.5    78.3  4596.5    76.8  4616.5      76  4656.5    75.7  4717.3    77.1
  4737.3    76.7  4757.3    76.8  4758.8   76.74  4767.3    76.4  4800.7   77.54
  4817.3    78.1  4851.8    78.2  4858.2   77.92  4881.8    76.9 4894.09   77.07
  4894.2   77.07 4894.31   77.07  4917.4   77.38  4925.7   77.29  4928.5   77.26
  4962.3    76.7  4974.4   73.81 4978.61      72  4978.7   71.96  4978.8   71.92
  4990.4   66.93  4990.5   66.18  4990.7   64.67    4993   62.73  4998.7    62.7
  5004.9   63.22  5009.2   64.35  5009.9   67.08    5010   67.47 5021.09   71.88
  5021.2   71.93  5021.3   71.97  5028.5   74.83  5051.6   76.86  5059.1   77.52
  5079.3   77.38 5103.89    77.2    5104    77.2 5104.11    77.2  5109.1   77.17
    5120   77.09  5168.5   77.03  5187.7   77.07  5211.8   77.12    5239   77.29
  5239.9   77.28  5260.4   77.12  5302.3    76.8  5308.8    76.9  5338.8    77.4
  5358.8    77.4  5378.8    77.8
BR D #Mann= 3
  4546.5     .99  4974.4     .02  5028.5      .1
BR D Banks=4974.4,5028.5
BC Design=,, 0 ,, 0 ,,,,,,

Type RM Length L Ch R = 1 ,1258.3  ,116.7,116.7,116.7
BEGIN DESCRIPTION:
Downstream Section of Bridge/Culvert/Weir
END DESCRIPTION:
XS GIS Cut Line= 6
      3117615.69      13911494.2      3117383.64     13911620.76
      3117310.64     13911661.71      3117218.05     13911711.57
      3117129.03      13911754.3      3116870.45     13911862.68
#Sta/Elev= 30
  4546.5   78.33  4596.5   76.83  4616.5   76.03  4656.5   75.73  4717.3   77.13
  4737.3   76.73  4757.3   76.83  4767.3   76.43  4817.3   78.13  4851.8   78.23
  4881.8   76.93  4917.4   77.41  4962.3   76.73  4974.4   73.84  4990.4   66.96
  4990.7    64.7    4993   62.76  4998.7   62.73  5004.9   63.25  5009.2   64.38
    5010    67.5  5028.5   74.86  5059.1   77.55    5120   77.12  5168.5   77.06
    5239   77.32  5302.3   76.83  5338.8   77.43  5358.8   77.43  5378.8   77.83
#Mann= 3 , 1 , 0
  4546.5     .99       0  4974.4     .02       0  5028.5      .1       0
#XS Ineff= 2 , 0
       0    4968    78.7    5031       0    76.3
Permanent Ineff=
       F       F
Bank Sta=4974.4,5028.5
XS Rating Curve= 0
Exp/Cntr=.5,.3

Type RM Length L Ch R = 1 ,1141.6  ,34.2,34.2,34.2
BEGIN DESCRIPTION:
Upstream Section of Bridge/Culvert/Weir
END DESCRIPTION:
XS GIS Cut Line= 5
      3117391.34     13911533.74      3117190.79     13911626.98
      3117160.69     13911643.26      3117138.03     13911655.52
      3116906.46     13911752.47
#Sta/Elev= 22
  4760.5   76.99  4833.4   77.42  4920.9   76.21    4944   75.42  4957.3   74.96
  4979.5   73.72  4985.4   70.03    4991   66.53  4991.3   63.29  4997.1   62.38
  5000.5   62.13    5005   62.45  5008.6   63.18  5008.8   66.72  5014.9   70.48
  5020.1   73.69  5041.1   74.19  5068.9   74.59  5099.1   75.03  5163.6   75.45
  5257.5   75.83  5292.7   77.11
#Mann= 5 , 1 , 0
  4760.5      .2       0    4944     .08       0  4979.5     .02       0
  5020.1     .08       0  5068.9      .2       0
#XS Ineff= 2 , 0
       0  4984.8    70.3  5014.8       0    70.3
Permanent Ineff=
       F       F
Bank Sta=4979.5,5020.1
XS Rating Curve= 0
Exp/Cntr=.5,.3

Type RM Length L Ch R = 2 ,1124.5  ,,,
BEGIN DESCRIPTION:
CONCRETE CHECK STRUCTURE
Structure ID: P55-2
END DESCRIPTION:
Bridge Culvert--1,0,-1,-1, 0
Deck Dist Width WeirC Skew NumUp NumDn MinLoCord MaxHiCord MaxSubmerge Is_Ogee
10,14.2,3,0, 22, 22, , , .95, 0, 1,1,,
  4760.5  4833.4  4920.9    4944  4957.3  4979.5  4985.4    4991  4991.3  4997.1
  5000.5    5005  5008.6  5008.8  5014.9  5020.1  5041.1  5068.9  5099.1  5163.6
  5257.5  5292.7
   76.88   77.31    76.1   75.31   74.85   73.61   70.29    70.3    70.3   70.32
   70.33   70.34   70.35   70.35   70.38   73.58   74.08   74.48   74.92   75.34
   75.72      77
   76.88   77.31    76.1   75.31   74.85   73.61   69.92   66.42   63.18   62.27
   62.02   62.34   63.07   66.61   70.37   73.58   74.08   74.48   74.92   75.34
   75.72      77
  4760.5  4833.4  4920.9    4944  4957.3  4979.5  4985.4    4991  4991.3  4997.1
  5000.5    5005  5008.6  5008.8  5014.9  5020.1  5041.1  5068.9  5099.1  5163.6
  5257.5  5292.7
   76.88   77.31    76.1   75.31   74.85   73.61   70.29    70.3    70.3   70.32
   70.33   70.34   70.35   70.35   70.38   73.58   74.08   74.48   74.92   75.34
   75.72      77
   76.86   77.29   76.08   75.29   74.83   73.59    69.9    66.4   63.16   62.25
      62   62.32   63.05   66.59   70.35   73.56   74.06   74.46    74.9   75.32
    75.7   76.98
BR Coef= 1 , 0 , 0 ,1.25, 0 ,,,.8,-1,2,0,
WSPro=,,,, 1 ,,,, 0 ,,,, 0 ,,,,-1 ,-1 ,-1 , 0 , 0 , 0 , 0 , 0
Culvert=1,4.5,,14.2,.015,.5,1,1,3,62.08,5000,62.2,5000,Culvert #1  , 0 ,10
Culvert Bottom n=.015
BR U #Sta/Elev= 22
  4760.5   76.88  4833.4   77.31  4920.9    76.1    4944   75.31  4957.3   74.85
  4979.5   73.61  4985.4   69.92    4991   66.42  4991.3   63.18  4997.1   62.27
  5000.5   62.02    5005   62.34  5008.6   63.07  5008.8   66.61  5014.9   70.37
  5020.1   73.58  5041.1   74.08  5068.9   74.48  5099.1   74.92  5163.6   75.34
  5257.5   75.72  5292.7      77
BR U #Mann= 5
  4760.5      .2    4944     .08  4979.5     .02  5020.1     .08  5068.9      .2
BR U Banks=4979.5,5020.1
BR D #Sta/Elev= 22
  4760.5   76.86  4833.4   77.29  4920.9   76.08    4944   75.29  4957.3   74.83
  4979.5   73.59  4985.4    69.9    4991    66.4  4991.3   63.16  4997.1   62.25
  5000.5      62    5005   62.32  5008.6   63.05  5008.8   66.59  5014.9   70.35
  5020.1   73.56  5041.1   74.06  5068.9   74.46  5099.1    74.9  5163.6   75.32
  5257.5    75.7  5292.7   76.98
BR D #Mann= 5
  4760.5      .2    4944     .08  4979.5     .02  5020.1     .08  5068.9      .2
BR D Banks=4979.5,5020.1
BC Design=,, 0 ,, 0 ,,,,,,

Type RM Length L Ch R = 1 ,1107.4  ,209.3,209.3,209.3
BEGIN DESCRIPTION:
Downstream Section of Bridge/Culvert/Weir
END DESCRIPTION:
XS GIS Cut Line= 5
      3117374.93     13911503.74      3117174.39     13911596.98
      3117144.29     13911613.26      3117121.63     13911625.52
      3116890.05     13911722.46
#Sta/Elev= 22
  4760.5   76.85  4833.4   77.28  4920.9   76.07    4944   75.28  4957.3   74.82
  4979.5   73.58  4985.4   69.89    4991   66.39  4991.3   63.15  4997.1   62.24
  5000.5   61.99    5005   62.31  5008.6   63.04  5008.8   66.58  5014.9   70.34
  5020.1   73.55  5041.1   74.05  5068.9   74.45  5099.1   74.89  5163.6   75.31
  5257.5   75.69  5292.7   76.97
#Mann= 5 , 1 , 0
  4760.5      .2       0    4944     .08       0  4979.5     .02       0
  5020.1     .08       0  5068.9      .2       0
#XS Ineff= 2 , 0
       0  4984.8    70.3  5014.8       0    70.3
Permanent Ineff=
       F       F
Bank Sta=4979.5,5020.1
XS Rating Curve= 0
Exp/Cntr=.5,.3

Type RM Length L Ch R = 1 ,898.1   ,58,57.9,53.6
BEGIN DESCRIPTION:
Cross Section 898.1-Interpolated
END DESCRIPTION:
XS GIS Cut Line= 5
      3117424.85     13911413.73      3117344.86     13911417.36
      3117159.53     13911413.73      3117057.79     13911406.46
      3116866.94     13911399.76
#Sta/Elev= 25
  4694.5    76.4  4704.5    75.3  4762.4   75.55  4795.4   75.13    4831   75.34
  4875.6   75.23  4927.2    74.8  4933.4   74.75    4978   72.63  4990.8      66
  4991.2   62.38  4993.8   61.87    4999   61.66    5005   61.72  5008.8   62.35
  5009.3   65.91  5021.6   72.16  5035.6   74.94    5040   75.01  5069.1   75.44
  5116.8   75.22  5170.2   75.98    5238   74.77    5252    75.7  5252.9    76.5
#Mann= 5 , 1 , 0
  4694.5     .12       0  4927.2     .08       0    4978    .015       0
  5021.6     .08       0    5040      .1       0
#XS Ineff= 2 , 0
       0                  5170.2       0   75.98
Permanent Ineff=
       F       F
Bank Sta=4978,5021.6
XS Rating Curve= 0
Exp/Cntr=.5,.3

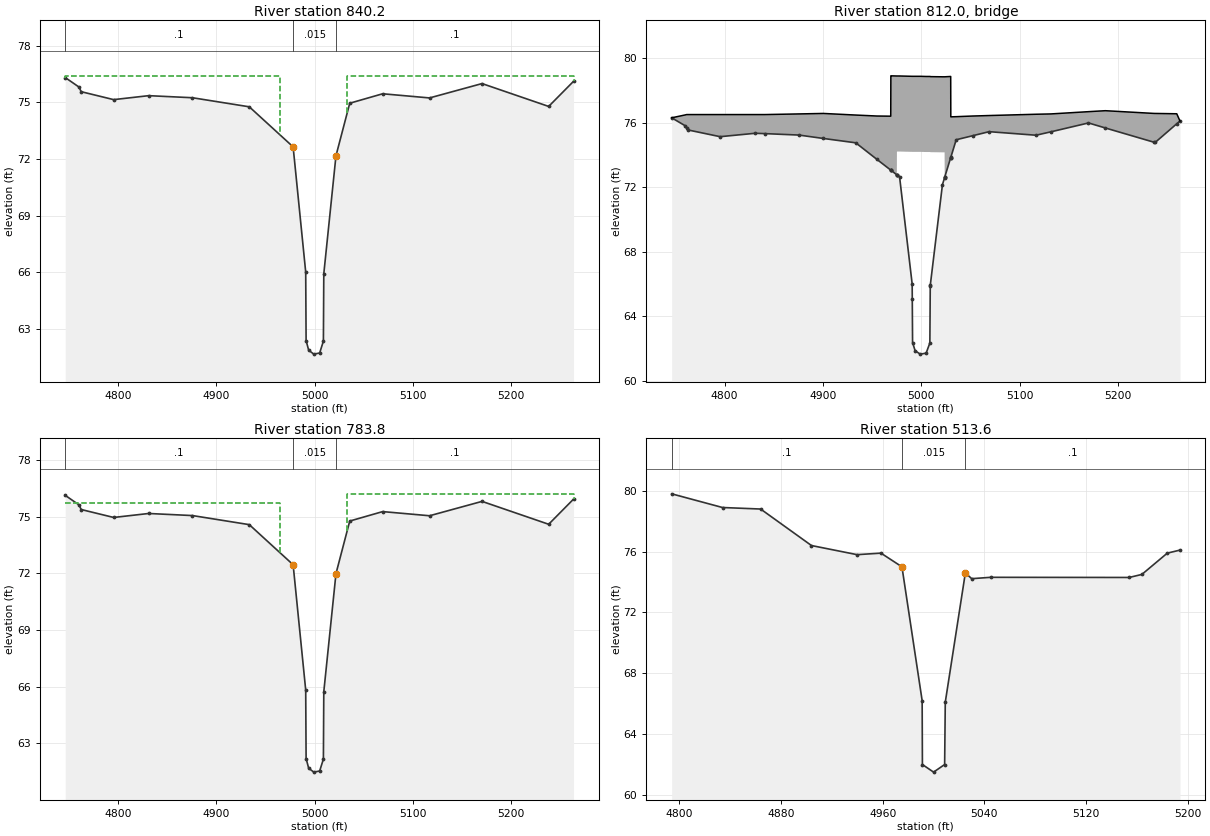
Type RM Length L Ch R = 1 ,840.2   ,56.4,56.4,56.4
BEGIN DESCRIPTION:
Upstream Section of Bridge/Culvert/Weir
END DESCRIPTION:
XS GIS Cut Line= 4
       3117376.9     13911355.64       3117180.7     13911342.55
      3117102.16     13911342.55      3116860.42      13911330.9
#Sta/Elev= 22
  4746.1   76.31    4760   75.81  4762.4   75.56  4795.4   75.14    4831   75.35
  4875.6   75.24  4933.4   74.76    4978   72.64  4990.8   66.01  4991.2   62.39
  4993.8   61.88    4999   61.67    5005   61.73  5008.8   62.36  5009.2   65.92
  5021.6   72.17  5035.6   74.95  5069.1   75.45  5116.8   75.23  5170.2   75.99
    5238   74.78  5263.3   76.11
#Mann= 3 , 1 , 0
  4746.1      .1       0    4978    .015       0  5021.6      .1       0
#XS Ineff= 2 , 0
       0    4965    76.4    5033       0    76.4
Permanent Ineff=
       F       F
Bank Sta=4978,5021.6
XS Rating Curve= 0
Exp/Cntr=.5,.3

Type RM Length L Ch R = 3 ,812.0   ,,,
BEGIN DESCRIPTION:
OLD GREENS ROAD
Structure ID: P55-1
END DESCRIPTION:
Bridge Culvert--1,0,-1,-1, 0
Deck Dist Width WeirC Skew NumUp NumDn MinLoCord MaxHiCord MaxSubmerge Is_Ogee
10,36.4,2.6,0, 45, 45, , , .95, 0, 1,1,,
  4746.1    4760  4761.3  4762.4  4795.4    4831  4840.8  4875.6  4900.4  4933.4
    4955 4968.99  4969.1 4969.21  4975.1 4975.21  4975.3    4978  4990.8  4990.9
  4991.2  4993.8    4999    5005  5008.8  5009.2  5009.3  5021.6 5023.79  5023.9
    5024 5029.89    5030 5030.11  5035.6  5052.4  5069.1  5116.8  5131.9  5170.2
  5187.3  5237.2    5238    5260  5263.3
    76.3   76.48    76.5    76.5    76.5    76.5    76.5   76.54   76.57   76.47
   76.41    76.4    78.9    78.9   78.89   78.89   78.89   78.89   78.87   78.87
   78.87   78.87   78.87   78.86   78.86   78.86   78.85   78.84   78.84   78.84
   78.84   78.86   78.86   76.36   76.37   76.41   76.44   76.52   76.54   76.68
   76.74   76.57   76.57   76.55    76.1
    76.3    75.8   75.66   75.55   75.13   75.34   75.32   75.23   75.02   74.75
   73.72   73.06   73.05   73.05   72.77   72.76   74.21   74.21   74.19   74.19
   74.19   74.19   74.19   74.18   74.18   74.18   74.17   74.16   74.16   72.62
   72.64   73.81   73.83   73.85   74.94   75.19   75.44   75.22   75.43   75.98
   75.67   74.78   74.77   75.93    76.1
  4746.1    4760  4761.3  4762.4  4795.4    4831  4840.8  4875.6  4900.4  4933.4
    4955 4968.99  4969.1 4969.21  4975.1 4975.21  4975.3    4978  4990.8  4990.9
  4991.2  4993.8    4999    5005  5008.8  5009.2  5009.3  5021.6 5023.79  5023.9
    5024 5029.89    5030 5030.11  5035.6  5052.4  5069.1  5116.8  5131.9  5170.2
  5187.3  5237.2    5238    5260  5263.3
    76.3   76.48    76.5    76.5    76.5    76.5    76.5   76.54   76.57   76.47
   76.41    76.4    78.9    78.9   78.89   78.89   78.89   78.89   78.87   78.87
   78.87   78.87   78.87   78.86   78.86   78.86   78.85   78.84   78.84   78.84
   78.84   78.86   78.86   76.36   76.37   76.41   76.44   76.52   76.54   76.68
   76.74   76.57   76.57   76.55    76.1
   76.12   75.62   75.48   75.37   74.95   75.16   75.14   75.05   74.84   74.57
   73.54   72.88   72.87   72.87   72.59   72.58   74.03   74.03   74.01   74.01
   74.01   74.01   74.01      74      74      74   73.99   73.98   73.98   72.44
   72.46   73.63   73.65   73.67   74.76   75.01   75.26   75.04   75.25    75.8
   75.49    74.6   74.59   75.75   75.92
Abutment Skew #Up #Dn= , 2 , 2
  4975.1  4990.9
   74.21    65.1
  4975.1  4990.9
   74.03   64.92
Abutment Skew #Up #Dn= , 2 , 2
  5009.3 5023.99
   65.96   74.16
  5009.3 5023.99
   65.78   73.98
BR Coef= 1 , 1 , 0 ,1.25, 0 ,,,.8,0,2,0,
WSPro=,,,, 1 ,,,, 0 ,,,, 0 ,,,,-1 ,-1 ,-1 , 0 , 0 , 0 , 0 , 0
BR U #Sta/Elev= 45
  4746.1    76.3    4760    75.8  4761.3   75.66  4762.4   75.55  4795.4   75.13
    4831   75.34  4840.8   75.32  4875.6   75.23  4900.4   75.02  4933.4   74.75
    4955   73.72 4968.99   73.06  4969.1   73.05 4969.21   73.05  4975.1   72.77
 4975.21   72.76  4975.3   72.76    4978   72.63  4990.8      66  4990.9    65.1
  4991.2   62.38  4993.8   61.87    4999   61.66    5005   61.72  5008.8   62.35
  5009.2   65.91  5009.3   65.96  5021.6   72.16 5023.79   72.59  5023.9   72.62
    5024   72.64 5029.89   73.81    5030   73.83 5030.11   73.85  5035.6   74.94
  5052.4   75.19  5069.1   75.44  5116.8   75.22  5131.9   75.43  5170.2   75.98
  5187.3   75.67  5237.2   74.78    5238   74.77    5260   75.93  5263.3    76.1
BR U #Mann= 3
  4746.1      .1    4978    .015  5021.6      .1
BR U Banks=4978,5021.6
BR D #Sta/Elev= 45
  4746.1   76.12    4760   75.62  4761.3   75.48  4762.4   75.37  4795.4   74.95
    4831   75.16  4840.8   75.14  4875.6   75.05  4900.4   74.84  4933.4   74.57
    4955   73.54 4968.99   72.88  4969.1   72.87 4969.21   72.87  4975.1   72.59
 4975.21   72.58  4975.3   72.58    4978   72.45  4990.8   65.82  4990.9   64.92
  4991.2    62.2  4993.8   61.69    4999   61.48    5005   61.54  5008.8   62.17
  5009.2   65.73  5009.3   65.78  5021.6   71.98 5023.79   72.41  5023.9   72.44
    5024   72.46 5029.89   73.63    5030   73.65 5030.11   73.67  5035.6   74.76
  5052.4   75.01  5069.1   75.26  5116.8   75.04  5131.9   75.25  5170.2    75.8
  5187.3   75.49  5237.2    74.6    5238   74.59    5260   75.75  5263.3   75.92
BR D #Mann= 3
  4746.1      .1    4978    .015  5021.6      .1
BR D Banks=4978,5021.6
BC Design=,, 0 ,, 0 ,,,,,,

Type RM Length L Ch R = 1 ,783.8   ,270.2,270.2,270.2
BEGIN DESCRIPTION:
Downstream Section of Bridge/Culvert/Weir
END DESCRIPTION:
XS GIS Cut Line= 4
       3117380.1     13911299.33       3117183.9     13911286.25
      3117105.36     13911286.25      3116863.61     13911274.59
#Sta/Elev= 22
  4746.1   76.12    4760   75.62  4762.4   75.37  4795.4   74.95    4831   75.16
  4875.6   75.05  4933.4   74.57    4978   72.45  4990.8   65.82  4991.2    62.2
  4993.8   61.69    4999   61.48    5005   61.54  5008.8   62.17  5009.2   65.73
  5021.6   71.98  5035.6   74.76  5069.1   75.26  5116.8   75.04  5170.2    75.8
    5238   74.59  5263.3   75.92
#Mann= 3 , 1 , 0
  4746.1      .1       0    4978    .015       0  5021.6      .1       0
#XS Ineff= 2 , 0
       0    4965    75.7    5033       0    76.2
Permanent Ineff=
       F       F
Bank Sta=4978,5021.6
XS Rating Curve= 0
Exp/Cntr=.5,.3

Type RM Length L Ch R = 1 ,513.6   ,0,0,0
BEGIN DESCRIPTION:
Cross Section 513.6
END DESCRIPTION:
XS GIS Cut Line= 2
      3117345.59     13911023.97      3116945.63     13911029.68
#Sta/Elev= 19
  4793.9    79.8  4833.9    78.9  4863.9    78.8  4903.9    76.4  4939.8    75.8
  4958.6    75.9  4975.1      75    4991    66.2  4991.2      62    5000    61.5
  5008.7      62  5009.2    66.1    5025    74.6    5030   74.22  5044.8   74.31
  5153.9    74.3  5163.9    74.5  5183.9    75.9  5193.9    76.1
#Mann= 3 , 1 , 0
  4793.9      .1       0  4975.1    .015       0    5025      .1       0
Bank Sta=4975.1,5025
XS Rating Curve= 0
Exp/Cntr=.3,.1

Chan Stop Cuts=-1